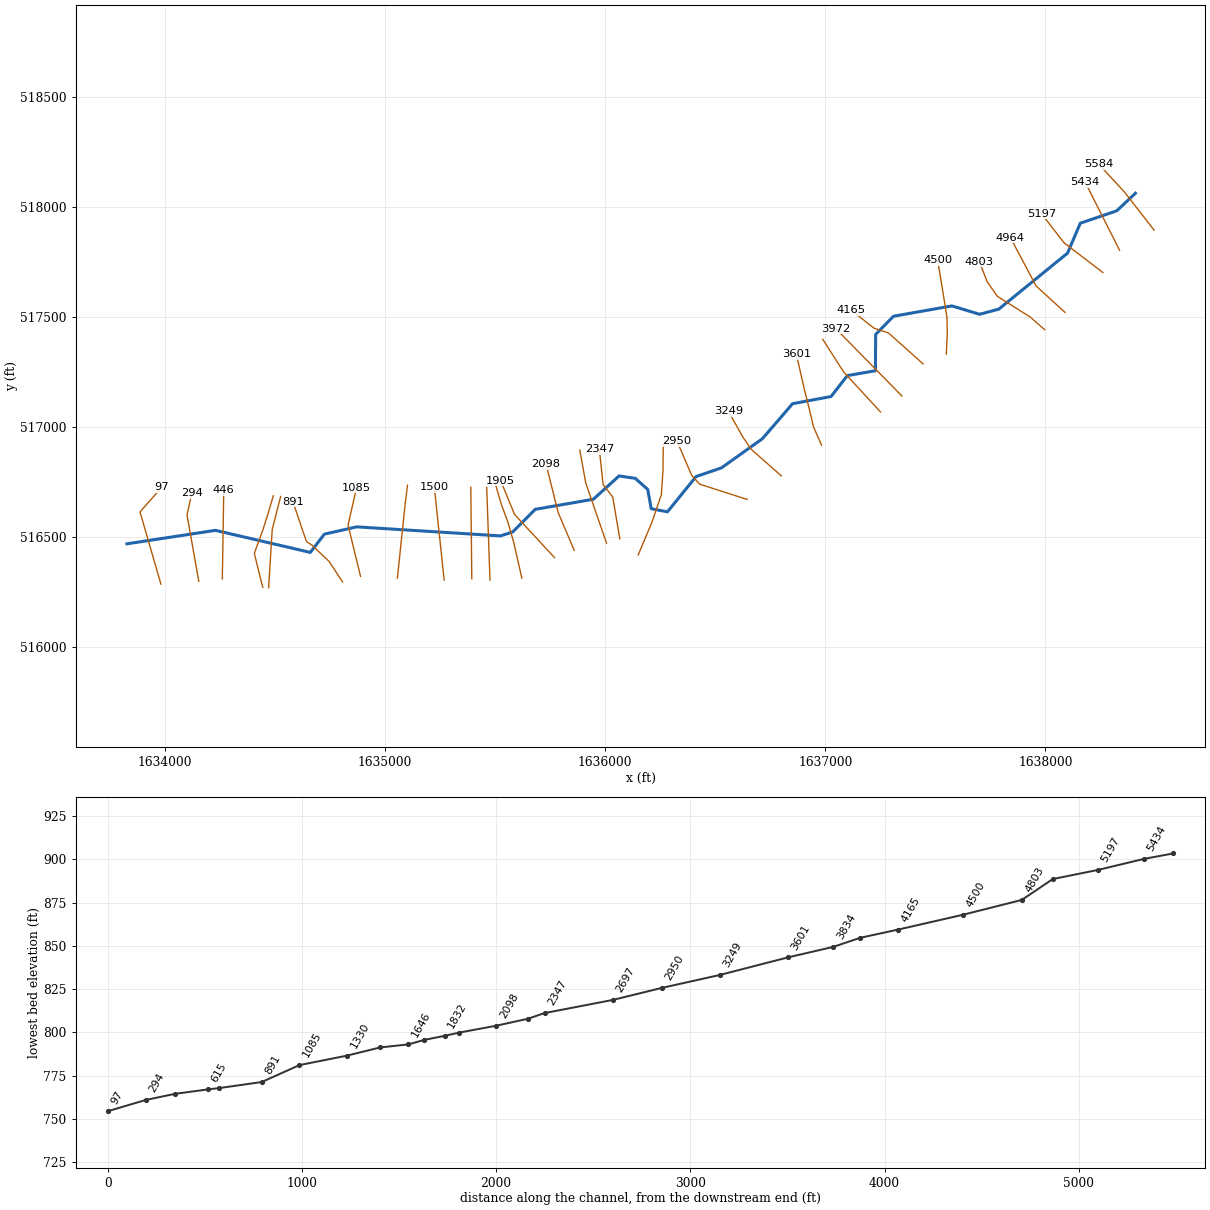
--- LeachRn.prj (project) ---

Proj Title=LeachRn
Current Plan=p01
Default Exp/Contr=0,0
English Units
Geom File=g01
Flow File=f01
Plan File=p01
BEGIN DESCRIPTION:
---------- MODELED AS PART OF WVEM CTP PROGRAM, 2025----------
Stream Name: Leach Run
Flood Zone: AFH
Marshall County, WV
HEC-RAS Version: RAS 6.6
Vertical Datum: NAVD88
Projection: NAD 1983 StatePlane West Virginia N FIPS 4701 (US Feet)
Terrain: 1-meter West Virginia FEMA R3 South Central (collected 2018-2019)
Land Use: 2024 NLCD
Hydrologic Method:
Duda et al., "Estimation of magnitude and frequency of floods for rural, unregulated streams in and near Virginia and West Virginia." September 8, 2025.
Additional Model Notes:
None
END DESCRIPTION:
DSS Export Rating Curves= 0
DSS Export Rating Curve Sorted= 0
DSS Export Volume Flow Curves= 0
DXF OffsetX= 0
DXF OffsetY= 0
DXF ScaleX= 0
DXF ScaleY= 0

--- LeachRn.p01 (plan) ---

Plan Title=Floodplain
Program Version=6.60
Short Identifier=Floodplain
Geom File=g01
Flow File=f01
Subcritical Flow
K Sum by GR= 0
Std Step Tol= 0.01
Critical Tol= 0.01
Num of Std Step Trials= 20
Max Error Tol= 0.3
Flow Tol Ratio= 0.001
Split Flow NTrial= 30
Split Flow Tol= 0.02
Split Flow Ratio= 0.02
Log Output Level= 0
Friction Slope Method= 1
Unsteady Friction Slope Method= 2
Unsteady Bridges Friction Slope Method= 1
Parabolic Critical Depth
Global Vel Dist= 0 , 0 , 0
Global Log Level= 0
CheckData=False
Encroach Param=-1 ,0,0, 0
Flow Ratio Tolerance=0.1
Flow Ratio Min Ratio=0.5
Flow Ratio Max Ratio=4
Flow Ratio Max Iterations= 10
Mapping Interval=1HOUR
Computation Time Step Use Courant=        0
Computation Time Step Use Time Series=    0
Computation Time Step Count To Double=0
Computation Time Step Max Doubling=0
Computation Time Step Max Halving=0
Computation Time Step Residence Courant=0
Run HTab= 0
Run UNet= 0
Run Sediment= 0
Run PostProcess= 0
Run WQNet= 0
Run RASMapper=-1
UNET Theta= 0
UNET Theta Warmup= 0
UNET ZTol= 0
UNET ZSATol= 0
UNET MxIter= 0
UNET Max Iter WO Improvement= 0
UNET MaxInSteps= 0
UNET DtIC= 0
UNET DtMin= 0
UNET MaxCRTS= 0
UNET WFStab= 0
UNET SFStab= 0
UNET WFX= 1
UNET SFX= 1
UNET Gravity=32.17405
UNET 1D Methodology=Finite Difference
UNET DSS MLevel= 1
UNET Pardiso=0
UNET DZMax Abort= 0
UNET Use Existing IB Tables= 0
UNET Froude Reduction=False
UNET Froude Limit= 0
UNET Froude Power= 0
UNET D1 Cores= 0
UNET WindReference=Eulerian
UNET WindDragFormulation=Hsu (1988)
UNET D2 Coriolis=0
UNET D2 Cores= 0
UNET D2 Theta= 1
UNET D2 Theta Warmup= 1
UNET D2 Z Tol= 0.01
UNET D2 Volume Tol= 0.01
UNET D2 Max Iterations= 20
UNET D2 Advanced Convergence=0
UNET D2 WS Max Tol=0.15
UNET D2 WS RMS Tol=0.002
UNET D2 WS Stall Tol=1
UNET D2 Equation= 0
UNET D2 RampUpFraction=0.1
UNET D2 TimeSlices= 1
UNET D2 Turbulence Formulation=Non-Conservative (original)
UNET D2 Eddy Viscosity=0.3
UNET D2 Transverse Eddy Viscosity=0.1
UNET D2 Smagorinsky Mixing=0
UNET D2 BCVolumeCheck=0
UNET D2 Cores=0
UNET D2 SolverType=PARDISO (Direct)
UNET D2 Minimum Iterations= 3
UNET D2 Maximum Iterations= 30
UNET D2 Restart Number= 10
UNET D2 Relaxation Coeff=1.3
UNET D2 SOR Precondition Iterations= 10
UNET D2 ILUT Maximum Fill= 8
UNET D2 ILUT Tolerance=1E-08
UNET D2 Convergence Tolerance=0.00001
PS Theta= 1
PS WS Tol= 0.01
PS Volume Tol= 0.01
PS Max Iterations= 20
PS Equation= 0
PS Advance Time Step=-1
PS Target Courant=0.9
PS Time Slices= 1
PS Iterate With 2D=0
PS Project Initial WSE from DS=-1
PS Ramp Up Initial WSE from US=-1
PS Cores=0
UNET D1D2 MaxIter= 0
UNET D1D2 ZTol=0.01
UNET D1D2 QTol=0.1
UNET D1D2 MinQTol=1
Write IC File= 0
Write IC File at Fixed DateTime=0
Write IC File at Sim End=0
Echo Input=False
Echo Parameters=False
Echo Output=False
Write Detailed= 0
HDF Write Warmup=0
HDF Write Time Slices=0
HDF Flush=0
HDF Compression= 1
HDF Chunk Size= 1
HDF Spatial Parts= 1
HDF Use Max Rows=0
HDF Fixed Rows= 1
Calibration Method= 0
Calibration Iterations= 20
Calibration Max Change=0.05
Calibration Tolerance=0.2
Calibration Maximum=1.5
Calibration Minimum=0.5
Calibration Optimization Method= 1
WQ AD Non Conservative
WQ ULTIMATE=-1
WQ Max Comp Step=1HOUR
WQ Output Interval=15MIN
WQ Output Selected Increments= 0
WQ Create Restart=0
WQ Fixed Restart=0
WQ System Summary=0
WQ Write To DSS=0
Sorting and Armoring Iterations= 10
XS Update Threshold= 0.02
Bed Roughness Predictor= 0
Processes Affected by Predictor=Sediment Only
Hydraulics Update Threshold= 0.02
Energy Slope Method= 1
Volume Change Method= 1
Sediment Retention Method= 0
Sediment TS Multiplier= 1
Warm Up Method= 0
XS Weighting Method= 0
Number of US Weighted Cross Sections= 1
Number of DS Weighted Cross Sections= 1
Upstream XS Weight=0
Main XS Weight=1
Downstream XS Weight=0
Number of DS XS's Weighted with US Boundary= 1
Upstream Boundary Weight= 1
Weight of XSs Associated with US Boundary= 0
Number of US XS's Weighted with DS Boundary= 1
Downstream Boundary Weight= 0.5
Weight of XSs Associated with DS Boundary= 0.5
Percentile Method= 0
Sediment Output Level= 3
Mass or Volume Output= 0
Output Increment Type= 1
Profile and TS Output Increment= 1
Transport Output Increment 1
XS Output Flag= 0
XS Output Increment= 10
Read HDF5 Sediment Hotstart= 0
Sediment Hotstart Type= 0
Write Gradation File= 0
Read Gradation Hotstart= 0
Write HDF5 File= 1
Write Binary Output= 1
Write DSS Sediment File= 0
DSS Sediment Output Type= 1
SV Curve= 0
Specific Gage Flag= 0
Subcell Erosion Methods= 0
Subcell Deposition Methods= 0
Advection Scheme= 1
Matrix Solver= 0
Implicit Weighting Factor= 1
Maximum Outer Loop Convergence Iterations= 5
Convergence Maximum Absolute= 0.001
Convergence RMSE= 0.0001
Grain Fractions Max Abs Error= 0.001
Max Subgrid Regions= 1
Max Subgrid Length Scale= 3.402823E+38
Initial Layer Thickness= 3
Min Layer Thickness= 0.1
Max Layer Thickness= 6
Number of Layers= 5

--- LeachRn.f01 (steady flow) ---

Flow Title=Flow
Program Version=6.60
Number of Profiles= 1
Profile Names=P100yr
River Rch & RM=LeachRn,Main,5584
     797
River Rch & RM=LeachRn,Main,2950
     887
Boundary for River Rch & Prof#=LeachRn,Main            , 1
Up Type= 0
Dn Type= 3
Dn Slope=0.02
DSS Import GetInterval= 0
DSS Import GetPeak= 0
DSS Import FillOption= 0

--- LeachRn.g01 (geometry) ---

Geom Title=Geometry
Program Version=6.60

River Reach=LeachRn         ,Main
Reach XY= 30
1638409.53302494518064.039721718     1638324.495      517984.148
     1638158.657      517927.698     1638100.856       517791.84
     1637788.086       517537.14     1637700.845      517513.912
     1637575.251      517551.996     1637310.018      517504.999
     1637228.853      517422.492     1637227.845       517257.32
     1637100.005      517235.292     1637026.152      517140.174
     1636851.294      517107.599     1636714.321      516948.536
     1636528.067      516815.976     1636412.618      516776.444
     1636282.774      516616.213      1636209.02      516630.349
      1636193.04      516718.239     1636136.188      516768.331
     1636063.048      516779.394     1635945.964      516673.372
     1635681.679      516627.584     1635579.611      516524.747
     1635523.944      516506.863     1634870.733       516547.97
     1634723.895      516514.866     1634659.771       516431.82
     1634228.701      516532.073     1633826.906      516470.912

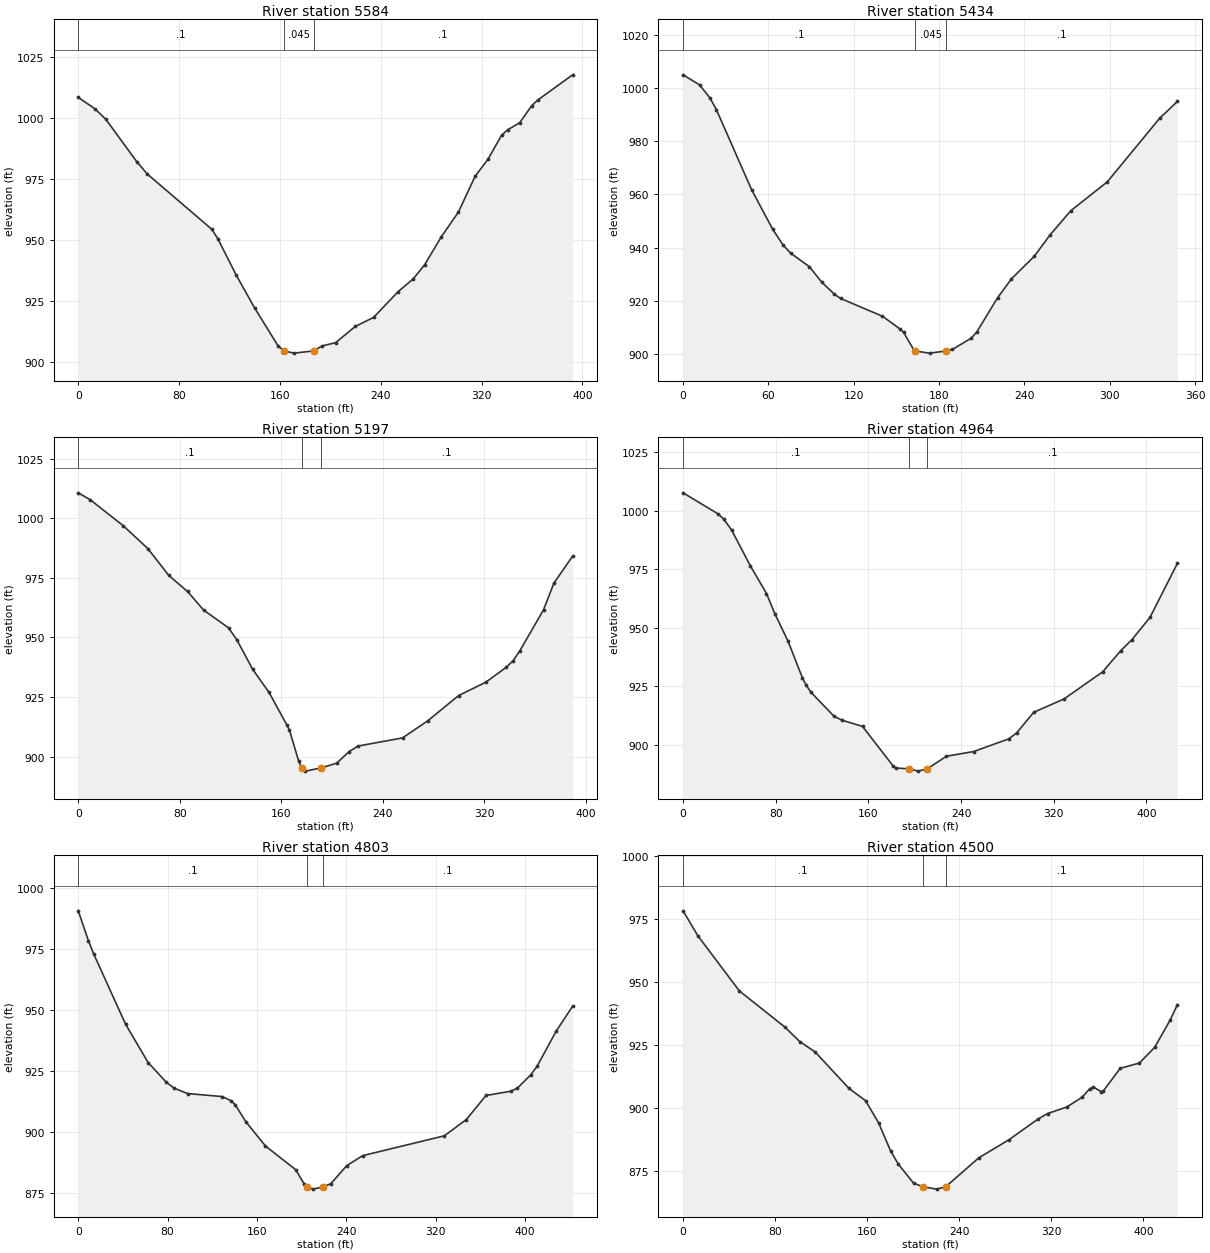
Type RM Length L Ch R = 1 ,5584    ,152.4,150.4,148.2
XS GIS Cut Line= 3
 1638493.9541001517896.4427461921638360.72223917518068.119612827
  1638241.943083518196.576466094
#Sta/Elev= 30
       0 1008.41    13.3 1003.71    21.9   999.4    46.5  981.98    54.8  976.96
     106  954.29   110.7  950.47   125.4  935.43   139.9  922.06   158.6  906.41
  163.35904.3738   171.1  903.47   186.8904.3746   193.4  906.41   204.2  907.75
   219.9  914.44   234.4  918.14   253.7  928.62   265.9  933.98   274.8  939.67
   288.2  951.27   301.6  961.28     315  976.09   325.1  982.99   335.9  992.84
   340.7   995.1   350.4  998.04   359.7 1004.93   364.5 1007.26   392.3 1017.67
#Mann= 3 ,-1,0
       0      .1       0  163.35    .045       0   186.8      .1       0
Bank Sta=163.35,186.8
XS Rating Curve= 0 ,0
Exp/Cntr(USF)=0,0
Exp/Cntr=0.3,0.1

Type RM Length L Ch R = 1 ,5434    ,231.9,237,240
XS GIS Cut Line= 2
1638337.35006419517804.7398213171638180.50672247518114.941097167
#Sta/Elev= 30
       0    1005    11.6 1001.21    18.9   996.3    23.4  991.91    48.3  961.64
      63  946.91    70.4  940.92    75.7  937.89    88.8  932.84    97.5  927.02
   106.4  922.48   110.8  920.88   140.2   914.2   152.8  909.31     155   908.2
   162.3  901.47   163.4 901.106   173.3  900.33  184.59 901.106   189.4  901.71
   202.7     906   206.5  908.27   221.1  921.13   230.9  928.28   246.9  936.73
   257.9   944.7   272.6  953.88   298.3  964.76   335.1  988.67   347.6  995.01
#Mann= 3 ,-1,0
       0      .1       0   163.4    .045       0  184.59      .1       0
Bank Sta=163.4,184.59
XS Rating Curve= 0 ,0
Exp/Cntr(USF)=0,0
Exp/Cntr=0.3,0.1

Type RM Length L Ch R = 1 ,5197    ,235.7,233.3,228.8
XS GIS Cut Line= 3
1638261.39980781517703.7086055861638084.65801364517839.012995989
1637982.48090046517970.971641661
#Sta/Elev= 30
       0 1010.62     9.4 1007.73    35.6  996.76    54.8  987.26    71.3     976
    86.1  969.26    98.8  961.45   118.4  954.03     125  948.97   137.4  936.64
   150.3  926.97   164.3  913.34   166.4   911.2   173.7  898.04  176.09 895.286
   178.8  893.94  191.32895.2871   203.6  897.27   213.4  902.13   220.5  904.46
   255.5  907.87   275.3  915.01   299.7  925.63   321.1  931.21   337.2  937.47
   342.6  940.24   347.9  944.36   366.6  961.58   374.8  972.79   389.5  984.06
#Mann= 3 ,-1,0
       0      .1       0  176.09    .045       0  191.32      .1       0
Bank Sta=176.09,191.32
XS Rating Curve= 0 ,0
Exp/Cntr(USF)=0,0
Exp/Cntr=0.3,0.1

Type RM Length L Ch R = 1 ,4964    ,154.8,160.3,162.7
XS GIS Cut Line= 3
1638089.30522376517522.4218062171637957.44063646 517643.24926947
1637841.26038333517862.249046615
#Sta/Elev= 30
       0 1007.74    30.2  998.72    34.9  996.59    41.8   991.9    58.1  976.46
      72  964.66    79.2  956.01    90.6  944.26     103  928.59   105.9  925.71
   110.4  922.39   130.1  912.23   137.1  910.47   154.9  907.78   181.2  890.94
   183.9  889.95  194.76889.6573   203.1  888.65  210.84 889.656   227.4  895.02
   250.8  897.02   281.2  902.46     288  905.02   302.8  913.87   328.8  919.51
   362.2  931.12   377.8  940.17   387.5  944.93   403.1  954.43   426.8   977.6
#Mann= 3 ,-1,0
       0      .1       0  194.76    .045       0  210.84      .1       0
Bank Sta=194.76,210.84
XS Rating Curve= 0 ,0
Exp/Cntr(USF)=0,0
Exp/Cntr=0.3,0.1

Type RM Length L Ch R = 1 ,4803    ,309.8,303.6,298.7
XS GIS Cut Line= 6
1637997.15792875517443.6701346781637930.54552917517501.921002418
1637866.87374051517541.9081271741637781.51728392517595.796470836
1637735.11908276517662.7107070831637700.34848301517753.050749511
#Sta/Elev= 30
       0  990.51     9.1  978.27    13.8  972.89    42.4  944.07    62.6  928.38
    78.9   920.3    85.9  917.89    97.9  915.69   128.9  914.45   136.6  912.82
   140.5  911.16     150  904.22   167.6  894.24   194.8   884.5   202.4  878.61
  204.95877.4494   210.3  876.55  219.26877.4501   226.2  878.76   240.4  886.15
   254.7  890.25   327.9  898.38   347.6  905.02   365.2   914.9   387.4  916.64
   393.3  917.89   405.2   923.3   410.9   926.8     428  941.16   442.8  951.45
#Mann= 3 ,-1,0
       0      .1       0  204.95    .045       0  219.26      .1       0
Bank Sta=204.95,219.26
XS Rating Curve= 0 ,0
Exp/Cntr(USF)=0,0
Exp/Cntr=0.3,0.1

Type RM Length L Ch R = 1 ,4500    ,323.1,334.8,342.5
XS GIS Cut Line= 6
1637549.77955842517333.1877440961637554.40881425517423.328639925
1637552.96426333517499.920350254 1637537.0751875517598.859128758
  1637524.864582517672.8189545871637510.61887559517759.104871258
#Sta/Elev= 30
       0  978.22    12.7  968.41    48.9  946.48    88.3  932.21   101.4  926.39
   114.6  922.36   144.1  907.87   158.5     903   169.8  894.26   180.4  882.99
     187  877.84   200.3  870.28  208.69 868.862   220.2  867.95  228.08868.8618
   256.8  880.32   283.4   887.6   308.1  895.65   316.7   897.9   333.3  900.47
   346.6  904.34   353.2  907.67   356.5  908.43   363.2  906.55   365.2  906.92
   379.8  915.82   396.4   917.9   409.7  924.11     423  934.79   429.5  941.08
#Mann= 3 ,-1,0
       0      .1       0  208.69    .045       0  228.08      .1       0
Bank Sta=208.69,228.08
XS Rating Curve= 0 ,0
Exp/Cntr(USF)=0,0
Exp/Cntr=0.3,0.1

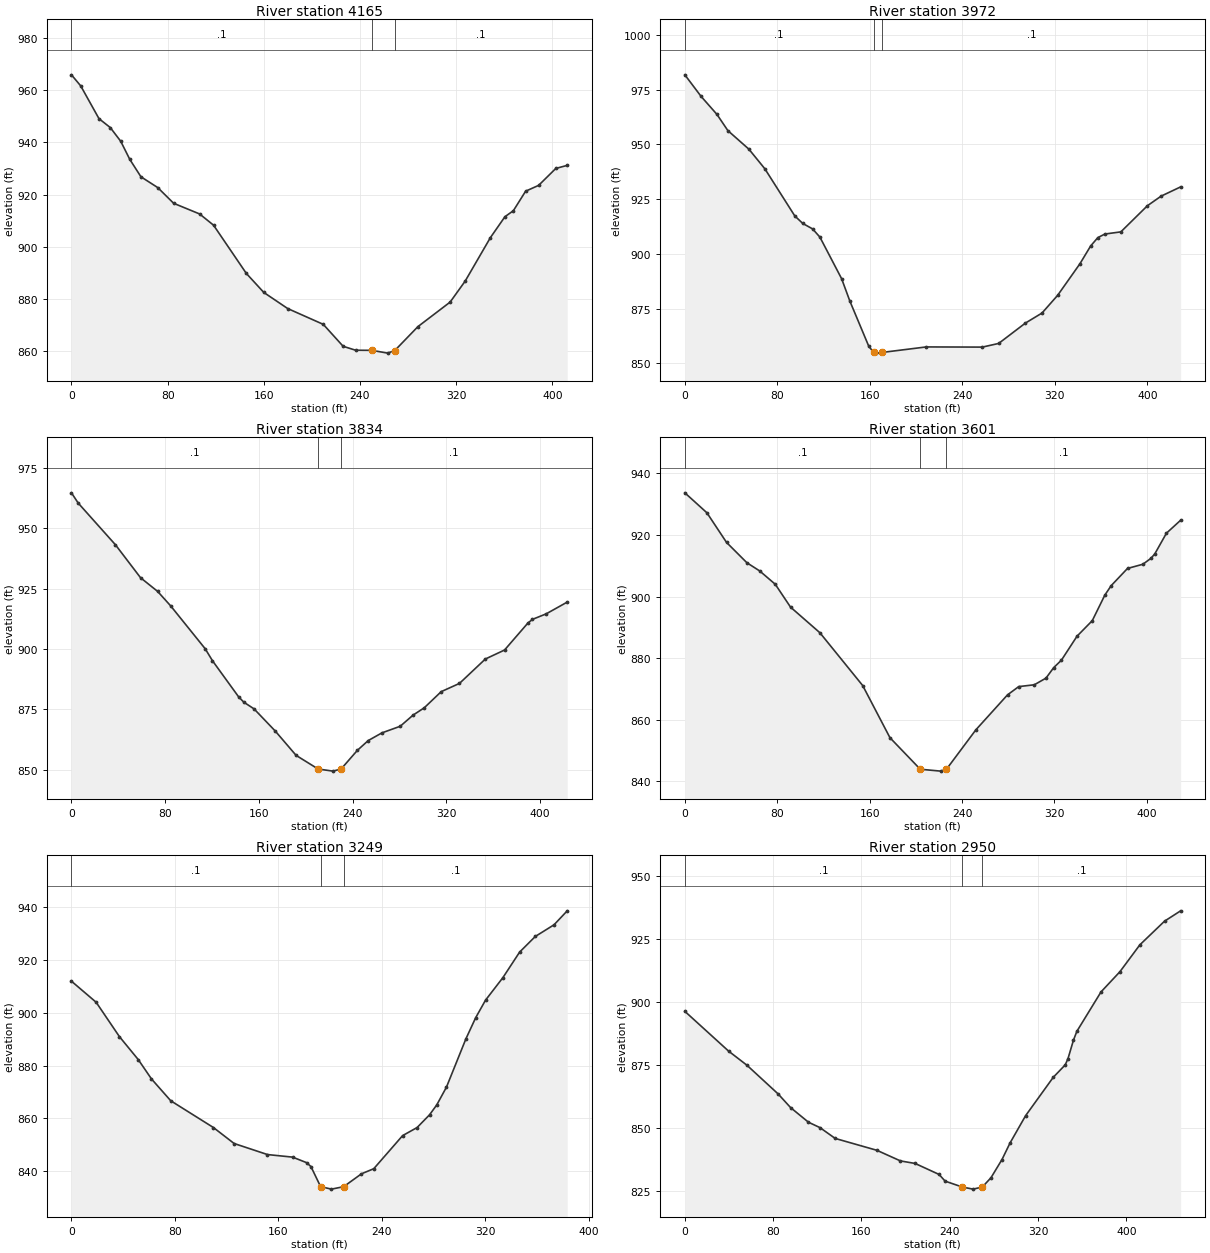
Type RM Length L Ch R = 1 ,4165    ,191.3,193.4,191.7
XS GIS Cut Line= 4
1637444.63231415517288.3002808661637287.60449959517428.725535875
 1637221.1171225517450.7610572191637118.00384937517532.621937642
#Sta/Elev= 30
       0  965.84     7.7  961.61    22.9  949.07    32.3  945.66      41  940.41
    48.5  933.51    57.8  926.83    71.8  922.69      85  916.69   106.6  912.61
   118.2  908.31   145.5  889.84     160  882.58   179.9  876.41   209.5  870.36
     226  861.97   236.4  860.47   249.9  860.42   263.1  859.36  268.95860.3489
   288.2   869.5     315  878.89   327.5  886.91   348.5  903.56   360.6  911.56
   367.6  913.85   377.8  921.32   388.6  923.54   402.9  930.02   412.4   931.2
#Mann= 3 ,-1,0
       0      .1       0   249.9    .045       0  268.95      .1       0
Bank Sta=249.9,268.95
XS Rating Curve= 0 ,0
Exp/Cntr(USF)=0,0
Exp/Cntr=0.3,0.1

Type RM Length L Ch R = 1 ,3972    ,132.6,138,139.2
XS GIS Cut Line= 2
1637348.26509539517142.3615389241637047.92002279  517448.4509162
#Sta/Elev= 30
       0  981.72      14   971.9    27.8  963.62    37.2  956.25    55.4  947.77
    69.2  938.81    95.1  917.28     102  913.85   110.5  911.36   116.8  907.62
   135.6  888.61   142.7  878.42     159  857.87  163.22  854.96   165.7  854.64
   170.7  854.96   208.8  857.47   257.3  857.39   271.4  859.06   294.6  868.38
   308.9  872.94   322.4  881.01   341.7  895.44     351  903.59   357.2  907.39
   363.3  909.02   377.1  910.01   400.1  921.96   411.9  926.32   428.8  930.55
#Mann= 3 ,-1,0
       0      .1       0  163.22    .045       0   170.7      .1       0
Bank Sta=163.22,170.7
XS Rating Curve= 0 ,0
Exp/Cntr(USF)=0,0
Exp/Cntr=0.3,0.1

Type RM Length L Ch R = 1 ,3834    ,238.2,232.7,227.9
XS GIS Cut Line= 3
1637250.67101373517070.3275204451637082.75289549517252.622089968
1636988.28177877517400.525860887
#Sta/Elev= 30
       0  964.69     5.8  960.42    37.6  943.15      59  929.52    73.6  923.85
    84.8  917.81   114.2  900.09   120.4  895.14   142.7   880.2   147.2  877.95
   155.9   875.2     174  866.02   191.8  855.94  210.61850.2838   223.3  849.41
  230.22850.2847   244.2  858.06   253.4  862.07   265.1  865.26   280.7  867.99
   291.7  872.62   301.2  875.63   315.7  882.33   331.3  885.75   353.4  895.85
   369.8  899.58   389.7  910.74   393.6  912.27   405.3  914.55   423.3  919.43
#Mann= 3 ,-1,0
       0      .1       0  210.61    .045       0  230.22      .1       0
Bank Sta=210.61,230.22
XS Rating Curve= 0 ,0
Exp/Cntr(USF)=0,0
Exp/Cntr=0.3,0.1

Type RM Length L Ch R = 1 ,3601    ,346.2,352,355.2
XS GIS Cut Line= 6
1636982.87944551516919.1259081661636946.16396776517002.990569845
1636929.13578659 517076.019623251636904.73360443517173.010899082
1636888.11159043517246.235490173 1636868.4938475517331.635253757
#Sta/Elev= 30
       0   933.7    19.1  927.22    36.1   917.6    53.7  911.01    64.8  908.34
    78.3  904.01    91.5   896.6   116.9  888.29     154  871.13   177.6   854.2
  203.84843.9625   221.6  843.35  226.53843.9622     252  856.76   279.4  868.11
   289.1  870.79   302.6  871.38   312.7  873.54   319.4  876.95   326.1  879.38
   339.6  887.16   352.8   892.2   363.7  900.51   369.2  903.58   383.3  909.15
   396.6  910.51   403.5  912.41   406.9  913.85     417  920.59   429.3   924.8
#Mann= 3 ,-1,0
       0      .1       0  203.84    .045       0  226.53      .1       0
Bank Sta=203.84,226.53
XS Rating Curve= 0 ,0
Exp/Cntr(USF)=0,0
Exp/Cntr=0.3,0.1

Type RM Length L Ch R = 1 ,3249    ,296.3,298.6,298.6
XS GIS Cut Line= 4
1636799.73785735 516780.021489591636662.82746659516900.829982166
1636626.84617766516953.9212683941636559.47152739517072.862628431
#Sta/Elev= 30
       0  911.95    19.1  903.97    37.1  890.94    51.7  882.22    61.9   874.9
    76.8  866.63   109.8  856.49   125.8  850.44   151.6  846.25     171  845.28
   181.8  843.19   185.2   841.7  192.69 834.078   201.1  833.15   210.5834.0741
   224.3  838.96   233.8  840.89   256.1  853.43   267.3  856.49   276.9   861.3
   282.5  865.06     290   871.8   305.1  890.17   312.6  898.11   320.2  904.75
   333.6  913.27   346.6  922.99   358.7   928.9   373.2  933.33   383.4  938.62
#Mann= 3 ,-1,0
       0      .1       0  192.69    .045       0   210.5      .1       0
Bank Sta=192.69,210.5
XS Rating Curve= 0 ,0
Exp/Cntr(USF)=0,0
Exp/Cntr=0.3,0.1

Type RM Length L Ch R = 1 ,2950    ,261.2,253.5,244.5
XS GIS Cut Line= 4
1636644.74489169516672.4830926471636428.91624872516742.074422058
1636392.77128108516782.0920648011636326.47130327516936.883388655
#Sta/Elev= 30
       0  896.31    39.6  880.52    56.3  874.88    84.5  863.49    95.8  858.06
     112  852.25   122.4  850.11   136.2  845.81     174  841.09   195.3  836.88
   208.6  835.87   230.3   831.5   235.8  828.84  251.34 826.502   261.1  825.67
  269.45826.5005   277.3  830.19   287.3  837.44   294.6  844.03   308.7  854.87
   333.7  870.09   344.6  875.06   347.1  877.56     352  884.83   355.1  888.37
     377  904.04   394.1  912.05   412.2  922.75   434.5  932.13   449.1  936.25
#Mann= 3 ,-1,0
       0      .1       0  251.34    .045       0  269.45      .1       0
Bank Sta=251.34,269.45
XS Rating Curve= 0 ,0
Exp/Cntr(USF)=0,0
Exp/Cntr=0.3,0.1

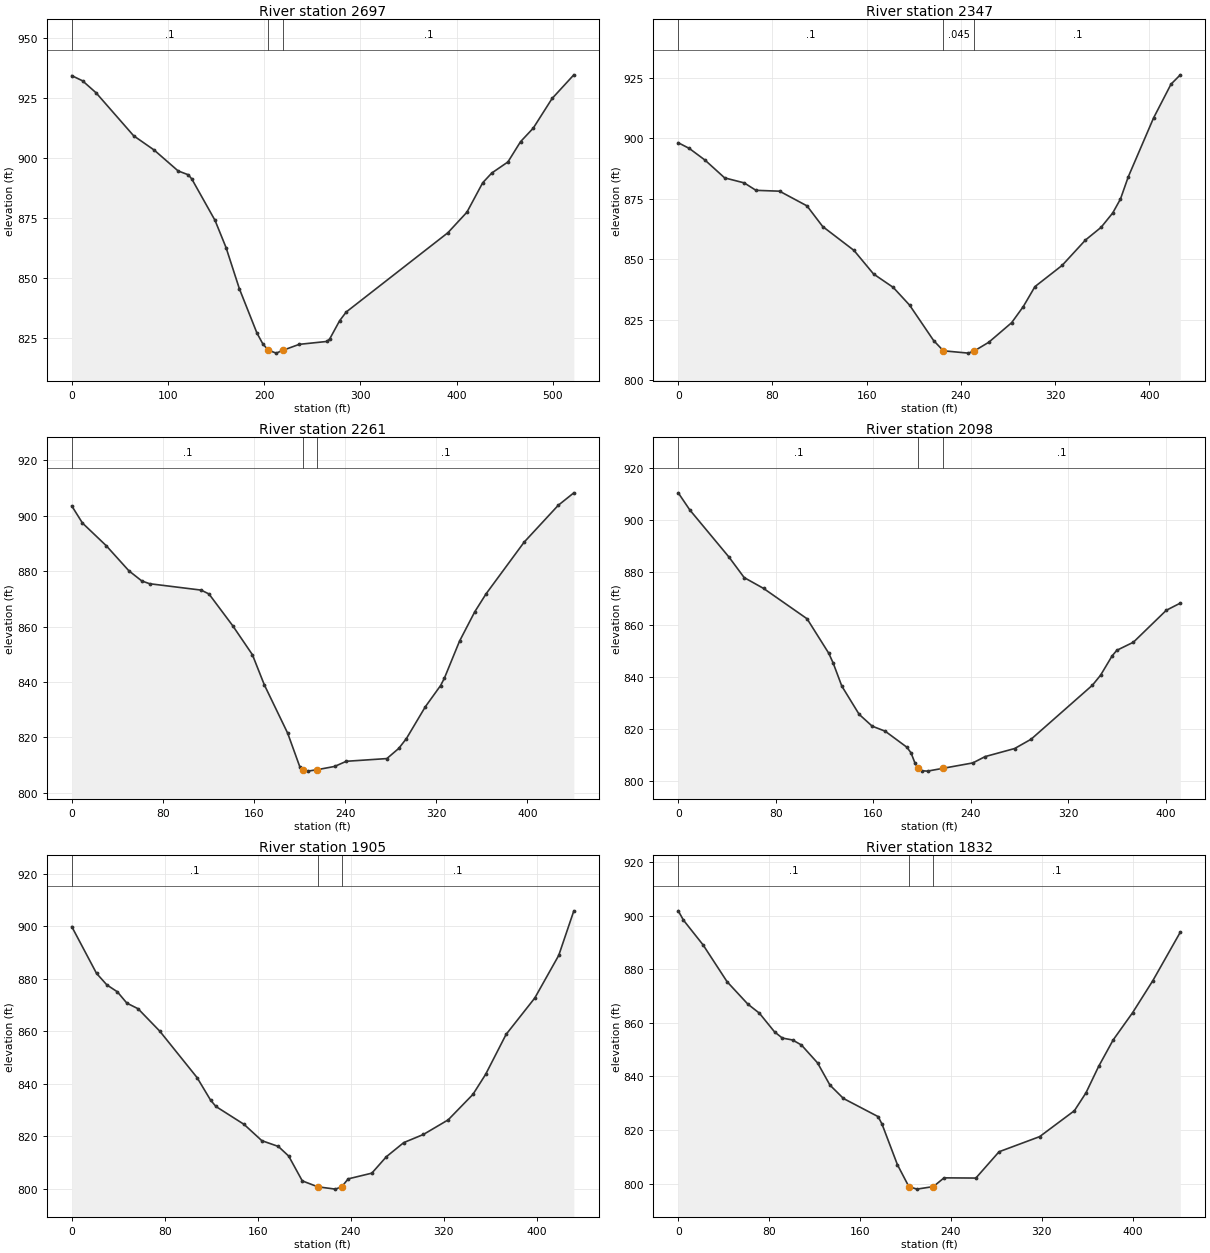
Type RM Length L Ch R = 1 ,2697    ,324.8,350.1,354.9
XS GIS Cut Line= 6
1636149.92704317516420.4809080961636183.71568951516501.194001257
1636212.67724575516570.3766056751636254.92322426516693.800899506
 1636262.5816735516805.3226580921636263.74046384516922.258119762
#Sta/Elev= 30
       0  934.19    11.2  932.04    25.2  927.07    64.3  909.16    85.6  903.22
   110.5  894.53   121.2   892.9   124.8  891.12   148.9  873.91   160.3  862.63
   174.2  845.43   192.4  827.05   198.5  822.55  204.14819.9335   212.4  818.68
  219.93819.9332   236.3  822.33   264.8  823.53   267.9   824.5   278.3  832.15
   285.2  835.81   390.8  868.79   410.6  877.35     427   889.6   436.4  893.65
   453.2  898.26   466.3  906.69   479.5  912.33   499.1  924.68   521.7  934.53
#Mann= 3 ,-1,0
       0      .1       0  204.14    .045       0  219.93      .1       0
Bank Sta=204.14,219.93
XS Rating Curve= 0 ,0
Exp/Cntr(USF)=0,0
Exp/Cntr=0.3,0.1

Type RM Length L Ch R = 1 ,2347    ,87.9,86,82.8
XS GIS Cut Line= 4
1636066.24666153516493.4546521971636033.95564455516683.935840878
1635990.26292761  516740.03100671635973.13906766516901.005927359
#Sta/Elev= 30
       0  898.14     9.4  895.78    22.7  890.97    39.4   883.6      56  881.53
      66  878.45      86   878.1   109.3  872.02   122.6  863.49   149.2  853.59
   165.8  843.85   182.5   838.3   196.4  830.96   216.8  816.31  225.07 812.074
   246.3  811.11  251.48 812.074   263.6   815.6     283  823.69   292.9  830.36
   302.8  838.62   325.9  847.41   345.7   857.9   358.9  863.12   368.8  869.07
   375.4  874.86     382  884.01   403.5   908.4   418.3  922.36   426.2  926.23
#Mann= 3 ,-1,0
       0      .1       0  225.07    .045       0  251.48      .1       0
Bank Sta=225.07,251.48
XS Rating Curve= 0 ,0
Exp/Cntr(USF)=0,0
Exp/Cntr=0.3,0.1

Type RM Length L Ch R = 1 ,2261    ,162.3,162.1,161.2
XS GIS Cut Line= 3
1636005.80995047 516474.147953481635911.43923094516747.412732657
1635884.35893751516896.764654009
#Sta/Elev= 30
       0  903.52     9.4  897.33    30.3  889.15    50.2  880.09    61.5  876.44
    68.4  875.44   113.6  873.14   120.5  871.74   141.3  860.31   158.6  849.85
   169.1  838.95   189.6  821.51   200.3  809.33  202.96  808.33   207.3  807.82
   215.4  808.33   230.8  809.51   241.1  811.37   276.7  812.35   287.1     816
   293.9  819.59   310.5  831.06   323.9  838.71   327.2  841.35   340.5  854.71
   353.9  865.32   363.9  871.84   397.2  890.42   427.2  903.74   440.9  908.24
#Mann= 3 ,-1,0
       0      .1       0  202.96    .045       0   215.4      .1       0
Bank Sta=202.96,215.4
XS Rating Curve= 0 ,0
Exp/Cntr(USF)=0,0
Exp/Cntr=0.3,0.1

Type RM Length L Ch R = 1 ,2098    ,185.7,193.7,195.8
XS GIS Cut Line= 3
1635858.85631396516441.5551014091635786.12799765516612.946646051
1635731.29006866516831.851315963
#Sta/Elev= 30
       0  910.55     9.5  903.98    41.7  885.87    54.1  878.04      70  873.89
   105.7  862.24   123.5  849.01   127.1  845.27   134.2  836.42   148.4   825.6
   159.1  821.06   169.8  819.12   187.6  812.97     191   810.8   194.3  806.81
  196.96 804.907   200.3  803.94   204.5  803.81  217.42804.9052   241.7  806.96
   251.8  809.39     276  812.48   289.5  816.05   339.8  836.77   346.5  840.61
   355.9  847.97   359.8  850.15   373.4  853.25   400.4   865.5   411.9  868.25
#Mann= 3 ,-1,0
       0      .1       0  196.96    .045       0  217.42      .1       0
Bank Sta=196.96,217.42
XS Rating Curve= 0 ,0
Exp/Cntr(USF)=0,0
Exp/Cntr=0.3,0.1

Type RM Length L Ch R = 1 ,1905    ,74,73.2,64.2
XS GIS Cut Line= 3
 1635769.2705893516408.3789172411635587.90030525516604.594455857
1635525.29205773516756.919676624
#Sta/Elev= 30
       0  899.89    21.3  882.06    30.2  877.66    39.2  875.03    47.4  870.71
      57  868.58    75.7  860.02   107.8   842.3   119.4  833.72     124  831.29
   148.2  824.47   163.5  818.25   177.7  816.05   186.6  812.38   198.3  802.91
  211.65800.6526   226.8  799.77  232.17800.6533   237.8  803.68   258.1  805.86
   270.7  812.16   285.6  817.52   302.5  820.62   323.8  826.19   345.1  835.91
     356  843.54   373.6  858.77   398.3  872.66   418.9  888.92   431.9  905.91
#Mann= 3 ,-1,0
       0      .1       0  211.65    .045       0  232.17      .1       0
Bank Sta=211.65,232.17
XS Rating Curve= 0 ,0
Exp/Cntr(USF)=0,0
Exp/Cntr=0.3,0.1

Type RM Length L Ch R = 1 ,1832    ,106.4,104.8,101.7
XS GIS Cut Line= 6
1635621.03740029516315.0217397311635601.70705839516400.359823654
1635585.13819388516473.5066589811635557.48601821516570.169851492
1635528.61829379516647.684788312 1635501.8073238516739.942149739
#Sta/Elev= 30
       0   901.8     4.6  898.32    21.9  889.06      43  875.33    61.3  866.96
    71.4   863.6    84.8  856.59    91.6  854.31   100.6  853.59   108.4  851.72
   122.6  845.04   133.5  836.75   145.4  831.75   175.9  824.98   179.3  822.21
   192.9  807.01  202.92798.8727     210  797.92  224.51798.8716   233.9  802.13
   261.9  802.05   282.3  811.87     318  817.51   348.6  827.19   358.8  833.87
   369.9  843.71   382.7   853.6   399.8  863.77   417.6  875.72   441.8  893.84
#Mann= 3 ,-1,0
       0      .1       0  202.92    .045       0  224.51      .1       0
Bank Sta=202.92,224.51
XS Rating Curve= 0 ,0
Exp/Cntr(USF)=0,0
Exp/Cntr=0.3,0.1

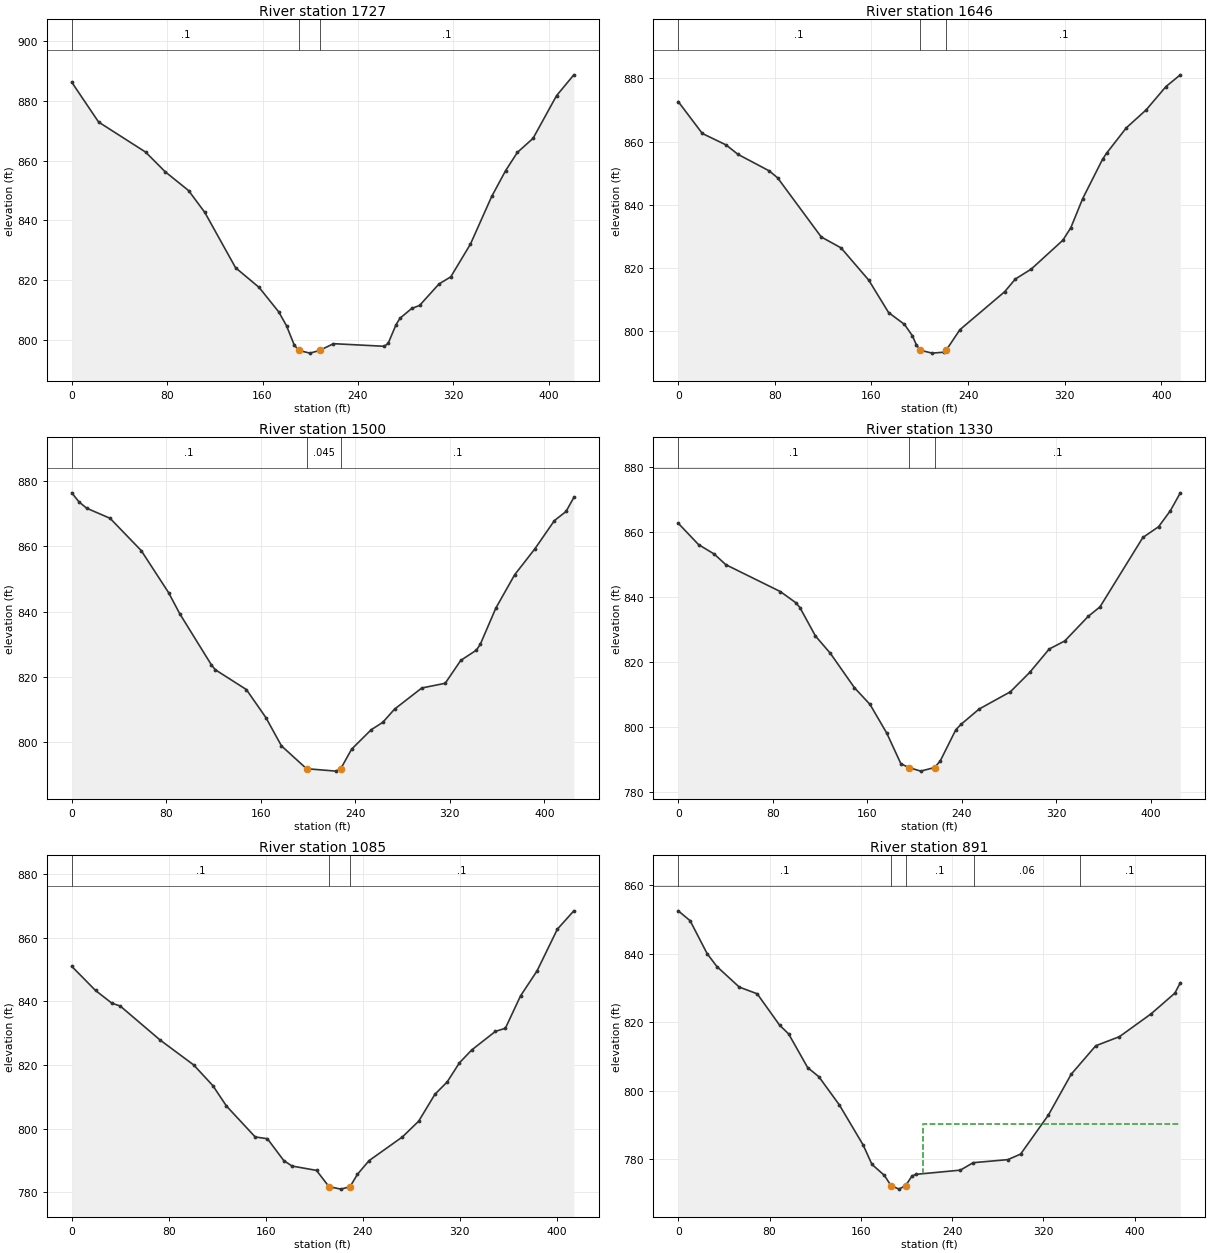
Type RM Length L Ch R = 1 ,1727    ,80,80.8,80.7
XS GIS Cut Line= 2
1635476.23817308516306.3984728291635461.39291851516727.229167491
#Sta/Elev= 30
       0  886.25    22.5  872.93    61.9  862.88    78.3  856.31      98  849.99
   111.6  842.67   137.4  824.16   157.1  817.59   173.5  809.44   180.1  804.76
   186.6  798.32  190.41796.4911   199.8  795.59  207.87796.4915   219.5  798.75
   262.1  797.88   265.4  798.89     272  805.13   275.3  807.27   285.1  810.54
   291.7  811.54     308  818.74   317.9  821.13   334.4   832.1   352.2  848.03
   363.9  856.68   373.7  862.75   386.9  867.48   406.6  881.76   421.1  888.73
#Mann= 3 ,-1,0
       0      .1       0  190.41    .045       0  207.87      .1       0
Bank Sta=190.41,207.87
XS Rating Curve= 0 ,0
Exp/Cntr(USF)=0,0
Exp/Cntr=0.3,0.1

Type RM Length L Ch R = 1 ,1646    ,144.7,146,147.3
XS GIS Cut Line= 2
1635393.62110419516312.2074854861635389.10298323516727.874613342
#Sta/Elev= 30
       0  872.66    19.9  862.57    39.6  858.93    49.5  855.94    75.4   850.7
    82.3   848.5   118.4  829.79   134.8  826.33   157.7  816.13   174.2  805.83
   187.3  802.11   193.8  798.54   197.1   795.7  200.32793.9339   210.2     793
   220.1   793.3  221.86793.9346   233.2  800.42   270.2  812.42   279.1  816.46
   292.3  819.62   318.5  828.77   325.1  832.76   334.9  841.96   351.3  854.37
   354.6  856.28     371  864.35   387.4  870.02   403.8  877.41   415.7  881.13
#Mann= 3 ,-1,0
       0      .1       0  200.32    .045       0  221.86      .1       0
Bank Sta=200.32,221.86
XS Rating Curve= 0 ,0
Exp/Cntr(USF)=0,0
Exp/Cntr=0.3,0.1

Type RM Length L Ch R = 1 ,1500    ,171.9,169.8,166.3
XS GIS Cut Line= 6
1635267.98392518516306.5218184291635258.78020342516393.536408171
 1635250.8911116516468.1202485111635240.37275992 516567.56558767
1635232.48334001 516642.149428011635223.27994634516729.164017752
#Sta/Elev= 30
       0  876.42       6   873.7    12.6  871.71    32.4  868.63    58.8  858.74
    81.9   845.9    91.5  839.35   118.1  823.81   121.4  822.29   147.8   816.2
   164.3  807.63   177.5  798.96  198.74791.9682   223.7  791.23  227.68791.9713
   236.9  797.96   253.4  803.88   263.3  806.18   273.2   810.2   296.3  816.68
   316.1  818.12   329.3  825.14   342.5  828.26   345.8  830.05     359  841.16
   374.9  851.34     392  859.27   408.5   867.9   418.4  870.72     425  875.02
#Mann= 3 ,-1,0
       0      .1       0  198.74    .045       0  227.68      .1       0
Bank Sta=198.74,227.68
XS Rating Curve= 0 ,0
Exp/Cntr(USF)=0,0
Exp/Cntr=0.3,0.1

Type RM Length L Ch R = 1 ,1330    ,241.8,245.5,247.7
XS GIS Cut Line= 6
1635055.53208363 516315.00144139 1635064.6268817516402.027514056
1635072.42115746516476.6215249751635082.81286895516576.079987467
1635090.60714471516650.673998386 1635101.5680808516737.592459724
#Sta/Elev= 30
       0  862.79    17.2  856.21    30.4  853.32    40.3  850.03    86.5  841.75
    99.7  838.29     103  836.85   116.2  828.08   128.8  822.76   149.2  812.17
   162.4  807.02   176.6  798.17   188.5  788.79  195.24787.6213   205.3  786.51
  217.03787.6212   221.8  789.62     235  799.22   239.3  800.86   254.7   805.6
   281.2  810.92   297.6  816.89   314.1  824.08   327.3  826.57   347.1  834.12
   357.1  837.05   393.4   858.4   406.7  861.71   416.6  866.59   425.1  872.14
#Mann= 3 ,-1,0
       0      .1       0  195.24    .045       0  217.03      .1       0
Bank Sta=195.24,217.03
XS Rating Curve= 0 ,0
Exp/Cntr(USF)=0,0
Exp/Cntr=0.3,0.1

Type RM Length L Ch R = 1 ,1085    ,188.4,194.2,197.1
XS GIS Cut Line= 3
1634887.97607952516322.9417083591634831.32027707516556.019376671
1634870.04702811516725.986784024
#Sta/Elev= 30
       0  850.96    19.6  843.38    33.1  839.39    39.9  838.52    72.9  827.82
   100.6     820   116.4   813.5   127.6  807.11   151.3   797.4   161.4  796.83
   174.9  789.98   181.7  788.26   201.9  786.89  212.19781.7847     222  781.01
  229.58 781.782   235.7  785.68   245.3  789.97   272.8  797.41   286.2  802.35
   299.6  810.79   309.7  814.66   319.8  820.66   329.9  824.69   349.5  830.54
   357.7  831.51   370.3  841.74   383.8   849.5   400.6  862.63   414.2  868.39
#Mann= 3 ,-1,0
       0      .1       0  212.19    .045       0  229.58      .1       0
Bank Sta=212.19,229.58
XS Rating Curve= 0 ,0
Exp/Cntr(USF)=0,0
Exp/Cntr=0.3,0.1

Type RM Length L Ch R = 1 ,891     ,221.4,217.9,211.1
XS GIS Cut Line= 6
1634806.58219216516297.2229547391634745.49619342 516390.46117737
1634667.69532188516464.696302681 1634642.3413037516480.754632274
1634612.21489774516568.8816664851634580.96725684 516661.55405331
#Sta/Elev= 30
       0  852.56    10.4  849.68    25.3  840.06    33.9  836.27    53.5  830.27
    69.2  828.31    88.8  819.15    96.7   816.6   113.4  806.74   123.2  804.08
   141.2  795.82   162.1  784.07   169.7  778.46   180.7  775.21  186.35 772.275
   193.4  771.22  199.25772.2754   204.9  775.09   208.5  775.55   247.2  776.77
   258.4  778.95   288.8  779.84     300  781.47   324.3  792.86   344.3   804.8
   365.8  813.12   386.6  815.79   414.2  822.43   435.1  828.49   439.9  831.54
#Mann= 5 ,-1,0
       0      .1       0  186.35    .045       0  199.25      .1       0
  259.01     .06       0  352.15      .1       0
#XS Ineff= 2 , 0
                          214.25          790.33
Permanent Ineff=
       F       F
Bank Sta=186.35,199.25
XS Rating Curve= 0 ,0
Exp/Cntr(USF)=0,0
Exp/Cntr=0.3,0.1

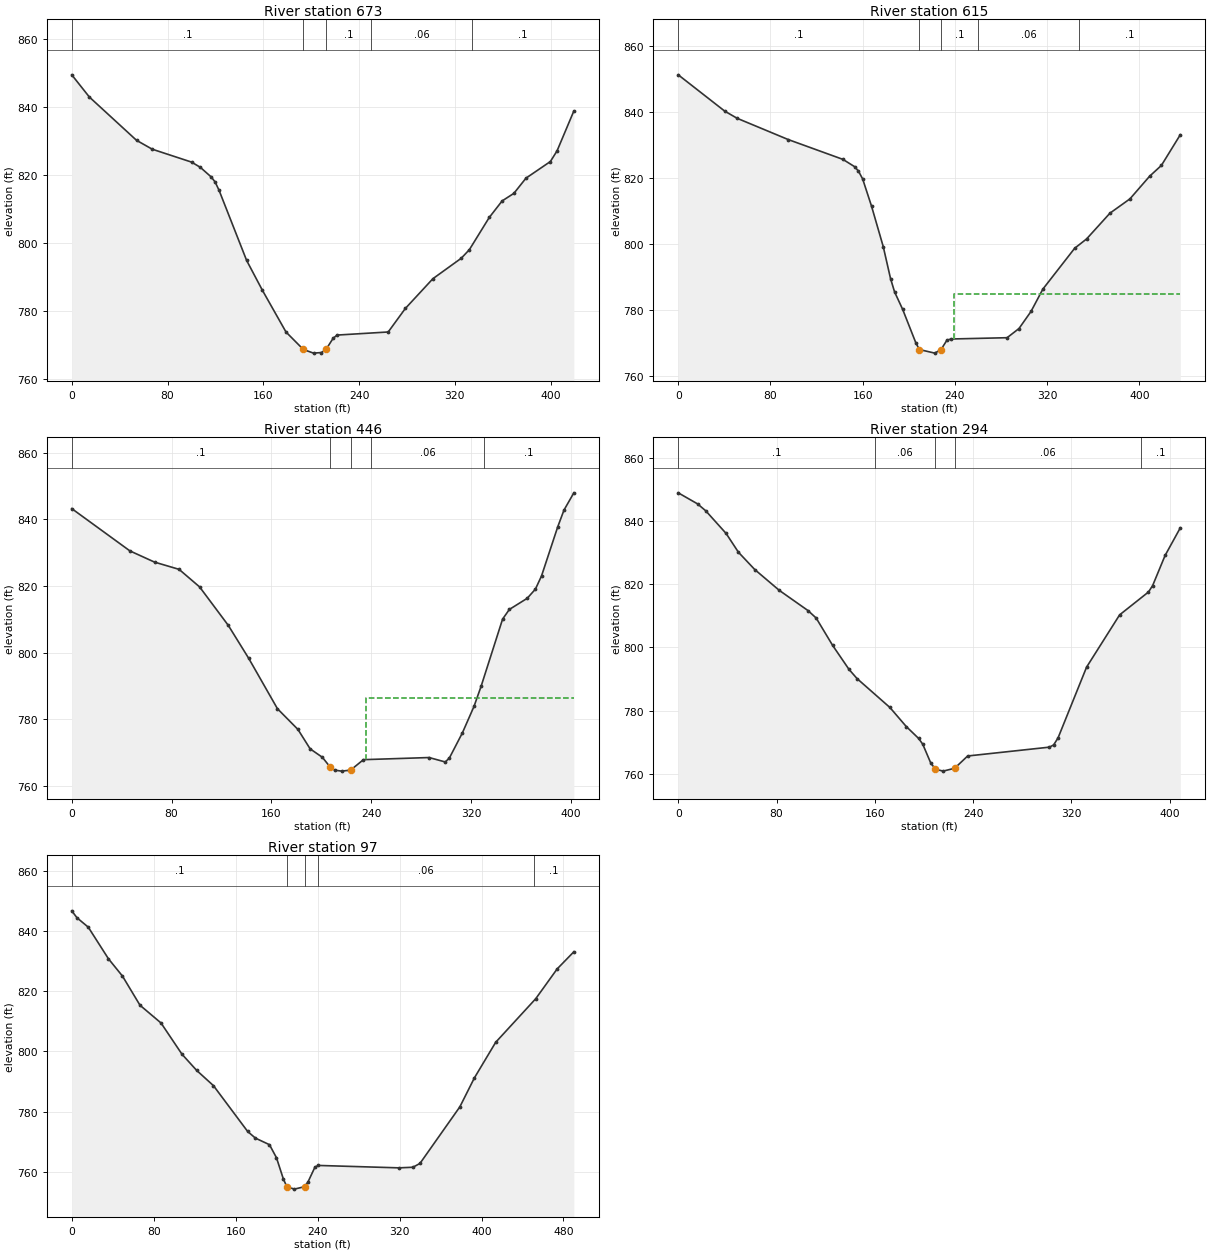
Type RM Length L Ch R = 1 ,673     ,60.8,58,55.4
XS GIS Cut Line= 3
1634470.39452907516271.6301766451634486.65976451516535.359351244
1634524.99924804516685.812779044
#Sta/Elev= 30
       0  849.59    14.7  843.06    54.1  830.33    67.2  827.72   100.1  823.92
   107.4  822.39   116.5  819.55   119.8  818.06   123.1   815.6   146.1     795
   159.2  786.27     179  773.95   193.5  768.81     202  767.74   208.6  767.91
   212.4768.8137   218.4  772.11   221.7  773.05   264.4  773.96   278.7  780.87
   301.7  789.62   325.4  795.64   332.2  798.16   348.8  807.63   359.6  812.51
   369.4  814.73   379.5   819.2   399.9  824.09   405.5  827.25   419.5  838.95
#Mann= 5 ,-1,0
       0      .1       0   193.5    .045       0   212.4      .1       0
     250     .06       0  334.23      .1       0
Bank Sta=193.5,212.4
XS Rating Curve= 0 ,0
Exp/Cntr(USF)=0,0
Exp/Cntr=0.3,0.1

Type RM Length L Ch R = 1 ,615     ,165.6,169.1,171.3
XS GIS Cut Line= 5
1634443.73472125516272.2996573461634405.35771087516427.482939693
1634444.03845181516533.5045132771634466.99148989516604.971233858
1634491.66204421516689.044228447
#Sta/Elev= 30
       0  851.26    40.3  840.27    51.1  838.09    95.4  831.65   142.8  825.65
   152.9  823.45   156.3   822.1   159.9  819.74   167.6  811.51   177.8   799.2
   184.1  789.56   187.6  785.51   194.6  780.23     206  770.12   209.1768.0438
   222.5  766.96   227.9768.0507     233  770.87   236.5  771.24   285.2  771.63
   295.5  774.41   305.9  779.57   316.2  786.35   343.8  798.73   354.1  801.54
   374.4  809.36   391.7  813.68   408.8  820.55     419  823.82   435.4  833.12
#Mann= 5 ,-1,0
       0      .1       0   209.1    .045       0   227.9      .1       0
  259.86     .06       0  347.78      .1       0
#XS Ineff= 2 , 0
                           239.4          784.75
Permanent Ineff=
       F       F
Bank Sta=209.1,227.9
XS Rating Curve= 0 ,0
Exp/Cntr(USF)=0,0
Exp/Cntr=0.3,0.1

Type RM Length L Ch R = 1 ,446     ,149.6,152,152.7
XS GIS Cut Line= 2
1634260.00423557516311.7737784221634266.56264487516714.022881816
#Sta/Elev= 30
       0  843.24    46.6  830.54    66.3  827.18      86     825   102.4  819.74
   125.4  808.19   141.8  798.27   164.8  783.16   181.2  776.95     191  771.11
   200.8  768.57   207.1765.6172   210.7  764.71   216.3  764.42   223.4764.7189
   233.7  767.86   286.3   768.5   299.3  767.17   302.6  768.38     313  775.91
   322.3  783.85     328   789.9   345.2  810.06   350.6  812.96   364.9   816.3
   371.5  819.06   376.4  823.02   389.3  837.67   394.4   842.8   402.3  847.98
#Mann= 5 ,-1,0
       0      .1       0   207.1    .045       0   223.4      .1       0
     240     .06       0     330      .1       0
#XS Ineff= 2 , 0
                          235.44          786.27
Permanent Ineff=
       F       F
Bank Sta=207.1,223.4
XS Rating Curve= 0 ,0
Exp/Cntr(USF)=0,0
Exp/Cntr=0.3,0.1

Type RM Length L Ch R = 1 ,294     ,195.2,196.2,197.2
XS GIS Cut Line= 3
1634153.09109083516300.2840764941634099.61054224516602.110598155
1634121.53596035516701.894828046
#Sta/Elev= 30
       0  848.92    15.7  845.43    22.4  843.23      39  836.05      49  830.12
    62.3  824.64    82.3  818.04   105.7  811.64   112.3  809.29   125.7  800.63
     139  793.05   145.6  790.12   172.3  780.99   185.6  774.97   195.6  771.23
     199   769.4   205.6  763.38   209.4761.4691   215.6  760.85     225761.7554
   235.6  765.64   302.2  768.44   305.6  769.15   309.2  771.38   332.4  793.76
   359.3   810.3   382.8  817.54   386.2  819.59   396.3  829.09   408.7  837.85
#Mann= 5 ,-1,0
       0      .1       0     160     .06       0   209.4    .045       0
     225     .06       0  376.53      .1       0
Bank Sta=209.4,225
XS Rating Curve= 0 ,0
Exp/Cntr(USF)=0,0
Exp/Cntr=0.3,0.1

Type RM Length L Ch R = 1 ,97      ,,,
XS GIS Cut Line= 3
1633980.99219919516287.8816982881633885.89526442516615.802163008
1633984.27140384516727.295121013
#Sta/Elev= 30
       0  846.68     5.1  844.37    16.1  841.26    35.8  830.77    49.5  825.02
    66.6  815.35    87.1  809.47   107.6  799.09     122   793.7   138.3  788.67
   171.7  773.46   179.3  771.25     193  769.07   199.8  764.76   206.6  757.64
  209.96 755.144   217.3  754.33  227.22755.1425   230.6  756.72   237.4  761.65
   240.8  762.19   319.4  761.39     333  761.59   339.9  762.86   378.8  781.62
     393  791.23   413.8  803.05   452.9  817.52   473.8   827.4   490.1  833.09
#Mann= 5 ,-1,0
       0      .1       0  209.96    .045       0  227.22      .1       0
     240     .06       0  451.43      .1       0
Bank Sta=209.96,227.22
XS Rating Curve= 0 ,0
Exp/Cntr(USF)=0,0
Exp/Cntr=0.3,0.1
LCMann Table=0

Chan Stop Cuts=-1
Use User Specified Reach Order=0
Composite Channel Slope=5